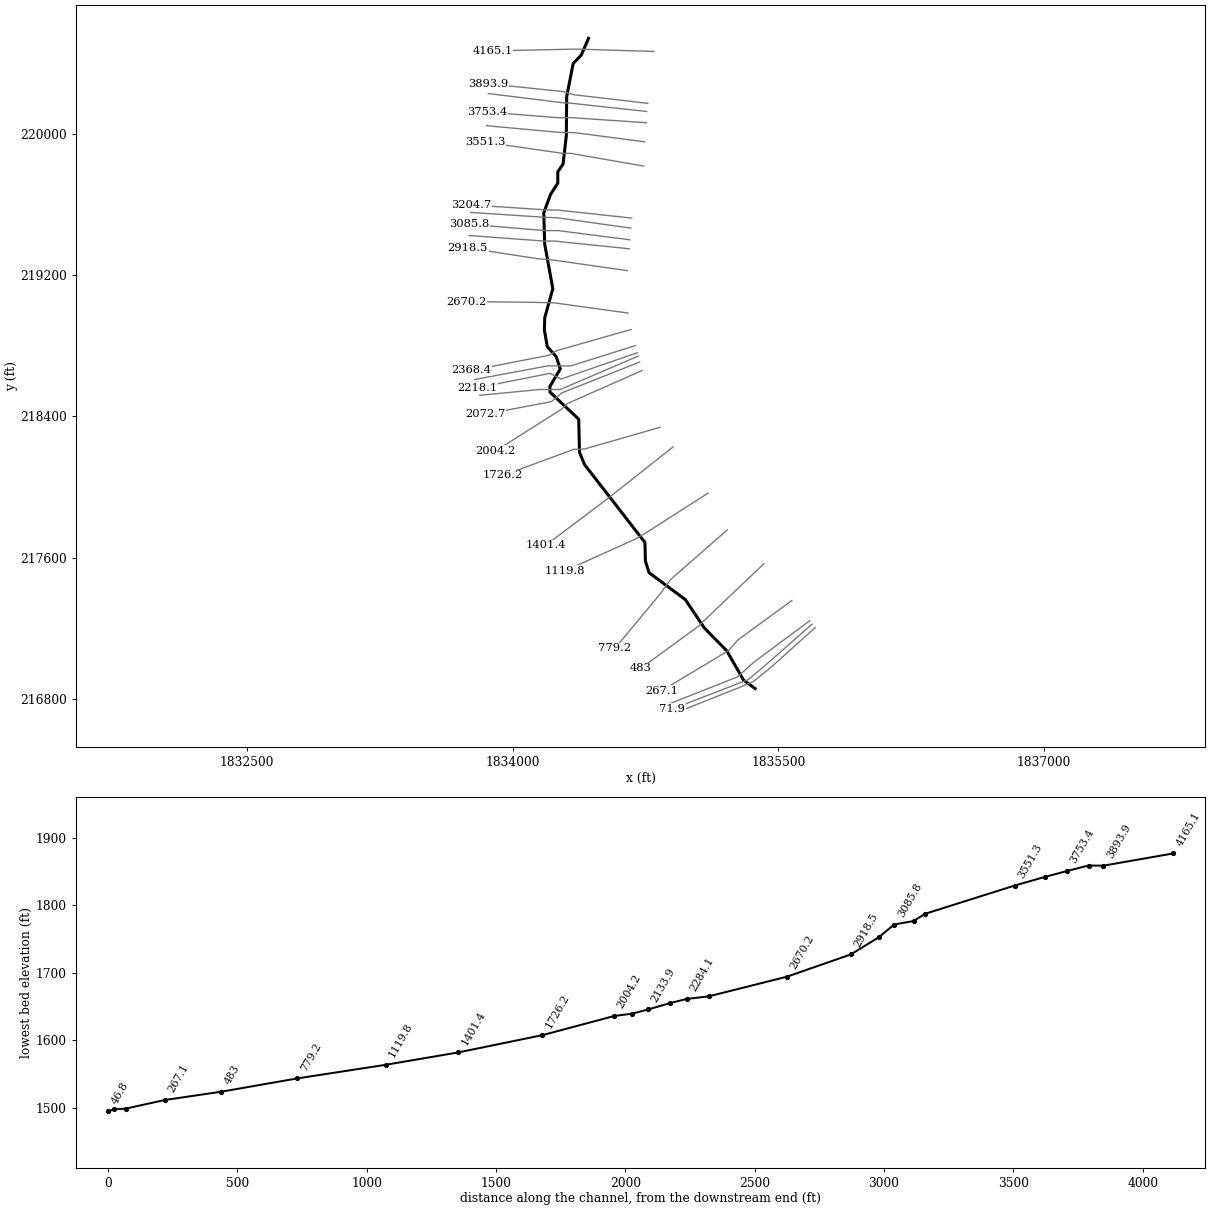
--- MeadowFk.prj (project) ---

Proj Title=MeadowFk
Current Plan=p01
Default Exp/Contr=0,0
English Units
Geom File=g01
Flow File=f01
Plan File=p01
BEGIN DESCRIPTION:
END DESCRIPTION:
DSS Export Rating Curves= 0
DSS Export Rating Curve Sorted= 0
DSS Export Volume Flow Curves= 0
DXF OffsetX= 0
DXF OffsetY= 0
DXF ScaleX= 0
DXF ScaleY= 0

--- MeadowFk.p01 (plan) ---

Plan Title=Floodplain
Program Version=4.00
Geom File=g01
Flow File=f01
K Sum by GR=0
Std Step Tol=0.01
Critical Tol=0.01
Num of Std Step Trials=20
Max Error Tol=0.3
Flow Tol Ratio=0.001
Split Flow NTrial=30
Split Flow Tol=0.02
Split Flow Ratio=0.02
Log Output Level=0
Friction Slope Method=1
Unsteady Friction Slope Method=2
Unsteady Bridges Friction Slope Method=1
Global Log Level=0
CheckData=False
Run HTab=0
Run UNet=0
Run PostProcess=0
UNET Theta=0
UNET Theta Warmup=0
UNET ZTol=0
UNET ZSATol=0
UNET MxIter=0
UNET MaxInSteps=0
UNET DtIC=0
UNET DtMin=0
UNET MaxCRTS=0
UNET WFStab=0
UNET SFStab=0
UNET WFX=0
UNET SFX=0
UNET DSS MLevel=0
UNET DZMax Abort=0
UNET Convert EG Bridges=0
UNET Use Existing IB Tables=0
UNET Froude Limit=0
UNET Froude Power=0
Write IC File=0
Echo Input=False
Echo Output=False
Write Detailed=0

--- MeadowFk.f01 (steady flow) ---

Flow Title=NFF Regression Equation
Program Version=4.00
Number of Profiles=1
Profile Names=P100yr
River Rch & RM=MeadowFk,Main      ,4165.1
557.5764
River Rch & RM=MeadowFk,Main      ,3893.9
559.2679
River Rch & RM=MeadowFk,Main      ,2368.4
611.9422
River Rch & RM=MeadowFk,Main      ,2368.4
662.5436
River Rch & RM=MeadowFk,Main      ,267.1
703.6203
Boundary for River Rch & Prof#=MeadowFk,Main      ,1
Up Type=0
Dn Type=3
Dn Slope=0.064659

--- MeadowFk.g01 (geometry) ---

Geom Title=USGS 10m DEM
Program Version=4.00

River Reach=MeadowFk        ,Main
Reach XY= 30
     1834427.841       220538.85     1834387.013      220444.438
     1834341.083      220395.955     1834304.639      220209.218
     1834302.372      219987.764     1834284.255      219828.202
     1834254.325      219783.547     1834254.413      219719.885
     1834213.498      219655.962     1834175.222      219551.342
     1834180.326      219375.275     1834226.256      219122.657
     1834180.656      218957.765     1834178.719       218888.67
     1834194.862      218795.037      1834245.23      218738.212
     1834268.477      218669.117     1834209.714      218569.027
     1834210.602      218537.224     1834372.442      218384.344
     1834376.962      218197.077     1834405.375      218127.337
     1834746.328      217686.939     1834748.911      217581.683
     1834769.575      217515.817     1834974.218      217363.912
     1835081.076      217203.778     1835208.661      217073.642
     1835303.074      216907.781     1835367.743      216860.969

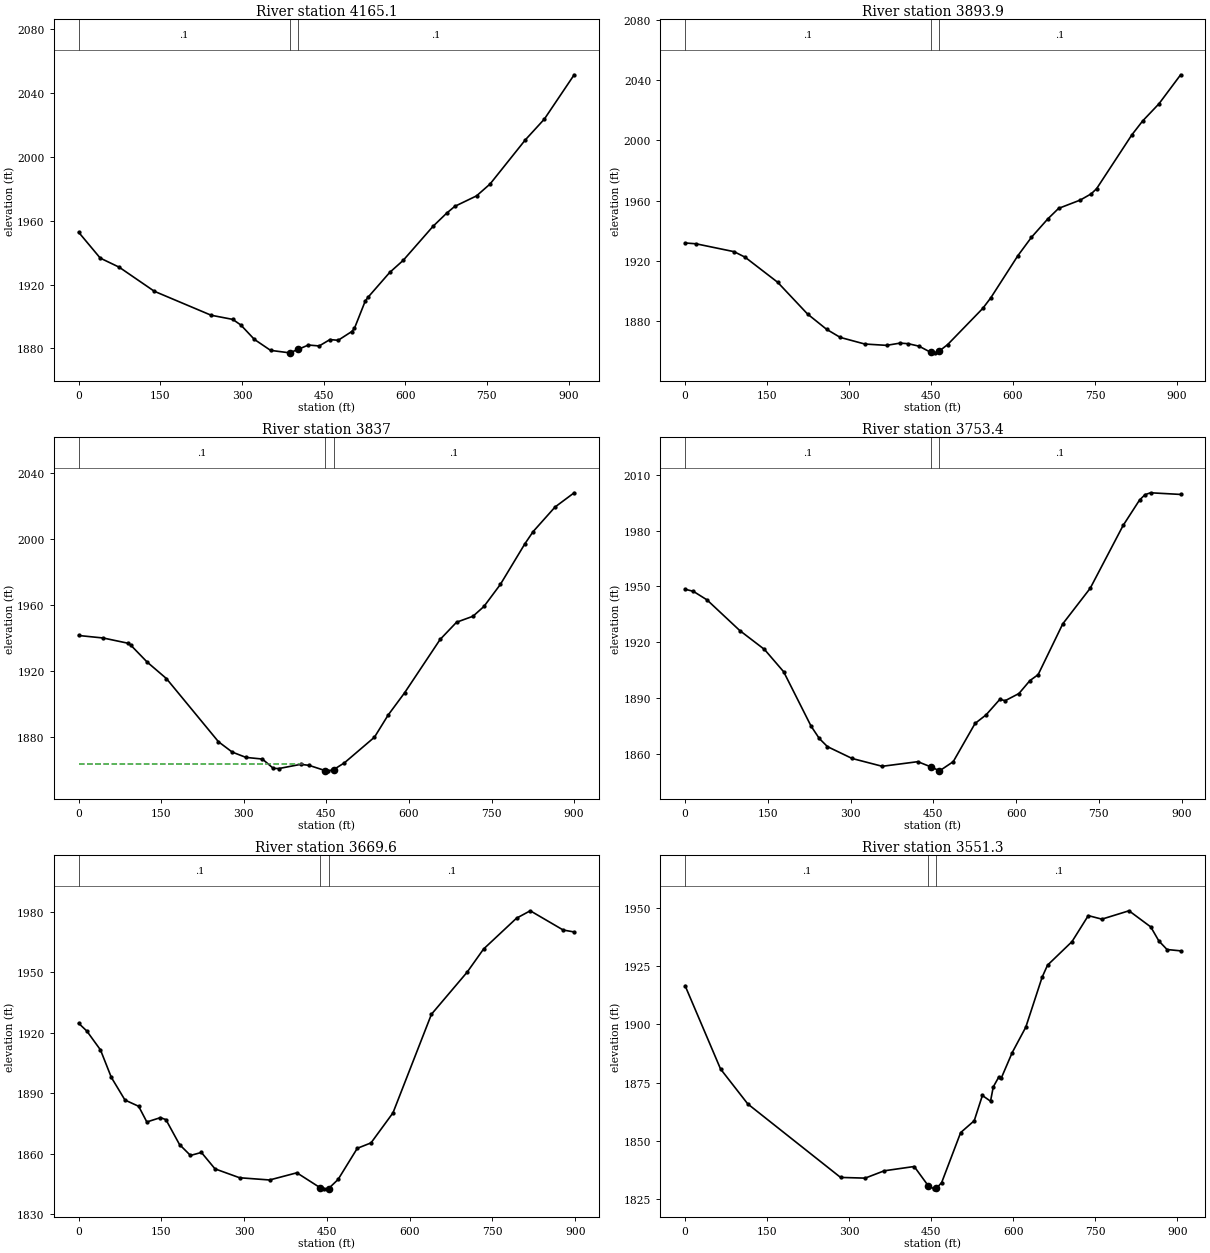
Type RM Length L Ch R = 1 ,4165.1  ,277.2,271.2,264.9
XS GIS Cut Line= 4
     1834796.028      220464.644     1834398.864      220476.815
     1834344.457      220477.732     1833886.034      220467.712
#Sta/Elev= 30
       0 1952.75    39.7 1936.54    74.5 1930.85   139.1 1915.75   243.4 1900.75
   283.1 1898.14     298 1894.62   322.8 1885.62   352.6 1878.74   387.4 1877.19
   387.7  1877.2   402.7 1879.29   422.1 1882.09   441.9  1881.5   461.7 1885.51
   476.7 1885.04   501.6 1890.51   506.6 1892.48   526.5 1909.62   531.5 1911.96
   571.4 1927.55   596.3 1935.15   651.1 1956.48     676 1964.67     691 1968.96
   730.9 1975.51   755.8 1982.96   820.6 2010.62   855.5 2023.62   910.3 2051.39
#Mann= 3 , 0 , 0
       0      .1       0   387.7    .045       0   402.7      .1       0
Bank Sta=387.7,402.7
XS Rating Curve= 0 ,0
Exp/Cntr=0.3,0.1

Type RM Length L Ch R = 1 ,3893.9  ,51.7,56.9,62.4
XS GIS Cut Line= 4
     1834762.752      220171.049     1834342.264      220220.076
     1834283.199      220237.871     1833863.826      220281.515
#Sta/Elev= 30
       0 1931.85    19.9 1931.31    89.6 1926.08   109.6 1922.46   169.3 1905.81
   224.1 1884.72     259 1874.57   283.9 1869.23   328.7 1864.85   368.6 1863.96
   393.4 1865.45   408.4 1865.05   428.1 1863.41   449.1 1859.39   456.6    1859
   464.1 1859.92   480.3 1864.44   544.6 1888.45   559.4 1895.52     609 1923.48
   633.8 1935.64   663.6 1947.79   683.4 1954.78   723.1 1960.31     743 1964.42
   752.9 1967.82   817.4 2003.52   837.2 2012.76     867 2024.12   906.7 2043.37
#Mann= 3 , 0 , 0
       0      .1       0   449.1    .045       0   464.1      .1       0
Bank Sta=449.1,464.1
XS Rating Curve= 0 ,0
Exp/Cntr=0.3,0.1

Type RM Length L Ch R = 1 ,3837    ,82.1,83.6,84.8
XS GIS Cut Line= 4
     1834756.501      220125.025     1834320.824      220172.734
     1834281.463       220174.67      1833862.31      220226.564
#Sta/Elev= 30
       0 1941.37    44.8 1939.84    89.6 1936.68    94.6 1935.53   124.5 1925.23
   159.4 1915.25     254 1876.89   278.9 1870.64   303.8 1867.41   333.7  1866.4
   353.6 1860.75   363.6 1860.64   403.4 1863.19   418.4 1862.59     448 1859.37
   453.1 1859.25     463 1859.97   482.7  1864.1   537.3 1879.67   562.2 1893.13
     592 1906.58   656.6    1939   686.4 1949.42   716.2 1953.04   736.1 1958.97
   765.9 1972.33   810.6 1997.07   825.5 2004.43   865.3 2019.33     900 2027.96
#Mann= 3 , 0 , 0
       0      .1       0     448    .045       0     463      .1       0
#XS Ineff= 2 , 0
          407.44 1863.48
Permanent Ineff=
       F       F
Bank Sta=448,463
XS Rating Curve= 0 ,0
Exp/Cntr=0.3,0.1

Type RM Length L Ch R = 1 ,3753.4  ,84.2,83.8,83.5
XS GIS Cut Line= 4
     1834753.966      220061.277     1834333.138      220090.062
     1834254.152      220089.898     1833858.005      220121.636
#Sta/Elev= 30
       0 1948.52    14.9  1947.4    39.7 1942.81    99.2 1926.32   143.9  1916.2
   178.6 1904.25   228.3 1875.06   243.2 1868.42     258 1864.04   302.7 1857.68
   357.3 1853.48   421.8 1855.96   445.9 1853.12   460.9 1851.08   461.3 1851.04
     486 1855.96   525.6 1876.48   545.5 1881.07   570.4 1889.38   580.3 1888.72
   605.1 1892.54     625 1899.48   639.9 1902.67   684.6 1929.97   734.3 1949.05
   793.9 1982.74   823.7 1996.39   833.6 1999.28   843.6  2000.3   898.2 1999.41
#Mann= 3 , 0 , 0
       0      .1       0   445.9    .045       0   460.9      .1       0
#XS Ineff= 2 , 0
          421.61 1855.44
Permanent Ineff=
       F       F
Bank Sta=445.9,460.9
XS Rating Curve= 0 ,0
Exp/Cntr=0.3,0.1

Type RM Length L Ch R = 1 ,3669.6  ,118.1,118.3,117.1
XS GIS Cut Line= 4
     1834744.703      219953.434     1834347.669      220005.556
     1834262.978      220006.744     1833851.727        220044.6
#Sta/Elev= 30
       0 1924.78    14.8 1920.92    39.6 1911.52    59.3 1897.86      84 1886.62
   108.8 1883.52   123.6 1875.73   148.3 1877.89   158.2 1876.89   182.9  1864.5
   202.7  1859.1   222.5 1860.59   247.2 1852.43   291.7 1848.02   346.1 1846.91
   395.5 1850.48     438 1843.02   445.3 1842.51     453 1842.65   470.2 1847.16
     505 1862.64   529.9 1865.34   569.7 1880.25   639.4 1929.23   704.1 1950.15
   733.9 1961.65   793.6 1976.96   818.5 1980.65   878.2 1971.09   898.1 1970.12
#Mann= 3 , 0 , 0
       0      .1       0     438    .045       0     453      .1       0
Bank Sta=438,453
XS Rating Curve= 0 ,0
Exp/Cntr=0.3,0.1

Type RM Length L Ch R = 1 ,3551.3  ,346.5,346.6,347.1
XS GIS Cut Line= 4
      1834739.23      219816.186     1834326.638      219888.165
     1834281.451      219888.322     1833844.206      219951.159
#Sta/Elev= 30
       0 1916.57    64.8 1880.88   114.7 1865.87   284.2 1834.41   329.1 1834.11
     364 1837.25   418.8 1839.09   444.3 1830.89     455 1829.52   459.3 1829.72
     469 1832.22   503.7 1853.62   528.5  1858.7   543.4 1869.52   558.3 1867.08
   563.3  1873.2   573.2 1877.36   578.2 1877.12     598 1887.94   622.8 1898.82
   652.6  1920.2   662.5 1925.37   707.2 1935.45     737  1946.6   761.8 1945.08
   811.4 1948.67   851.2 1941.75     866 1935.74   880.9 1932.07   905.8  1931.5
#Mann= 3 , 0 , 0
       0      .1       0   444.3    .045       0   459.3      .1       0
Bank Sta=444.3,459.3
XS Rating Curve= 0 ,0
Exp/Cntr=0.3,0.1

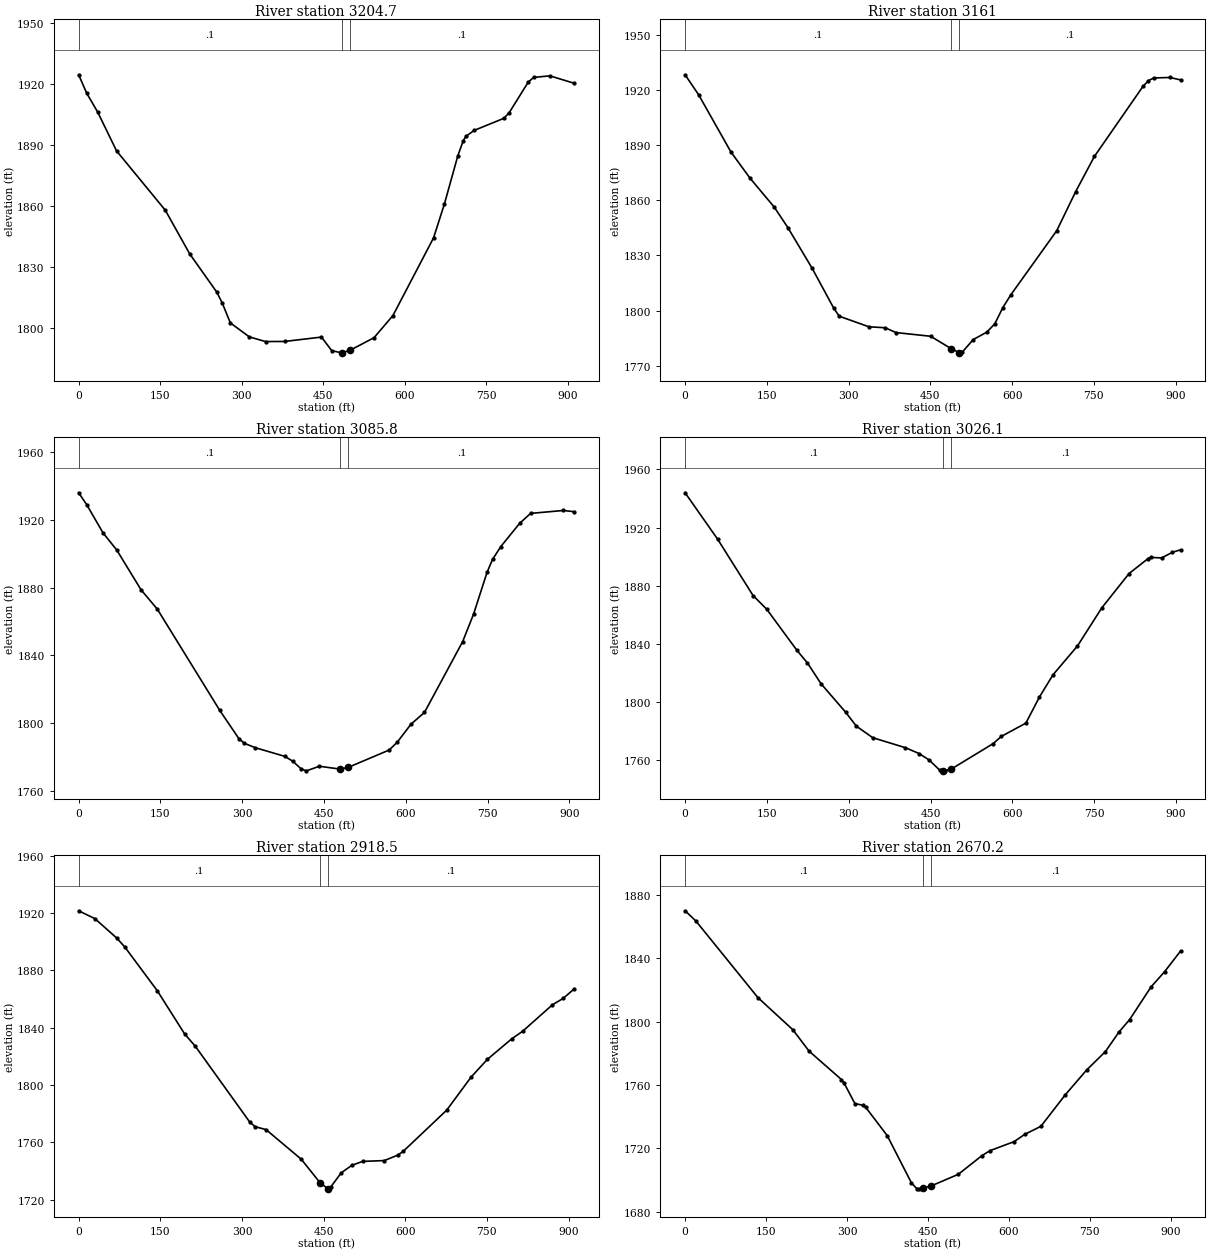
Type RM Length L Ch R = 1 ,3204.7  ,44.8,43.7,43.4
XS GIS Cut Line= 4
     1834671.946      219521.913      1834255.92      219567.182
     1834180.932      219568.812     1833764.007      219596.644
#Sta/Elev= 30
       0 1924.71      15 1915.55    34.9 1906.38    69.8 1887.16   159.4 1857.91
   204.3 1836.39   254.1 1817.52     264 1812.24     279 1802.36   313.9 1795.47
   343.8 1793.16   378.6 1793.21   446.6 1795.37   465.4 1788.69   483.6  1787.6
   498.6 1788.78   543.2 1795.06     578 1805.98   652.7 1844.29   672.6 1860.94
   697.4 1884.82   707.4 1892.26   712.4 1894.39   727.3 1897.27     782 1903.24
     792 1906.09   826.8 1921.09   836.7 1923.41   866.6 1924.18   911.3 1920.53
#Mann= 3 , 0 , 0
       0      .1       0   483.6    .045       0   498.6      .1       0
Bank Sta=483.6,498.6
XS Rating Curve= 0 ,0
Exp/Cntr=0.3,0.1

Type RM Length L Ch R = 1 ,3161    ,74.6,75.2,74.7
XS GIS Cut Line= 4
     1834666.856      219465.165     1834249.316      219523.945
     1834186.847      219526.115      1833762.72      219553.905
#Sta/Elev= 30
       0 1928.17    24.8 1917.32    84.3  1886.1   119.1 1871.97   163.7 1856.18
   188.5 1845.12   233.2 1822.92   272.8 1801.25   282.8 1796.92   337.3 1791.17
   367.1 1790.65   386.9 1788.03   450.5 1786.02   488.3 1779.26   503.3 1777.08
   503.9 1777.01   508.9 1777.52   528.6 1784.22   553.4 1788.23   568.2 1792.77
     583  1801.6   597.8 1808.63   681.9 1843.42   716.4 1864.52     751 1883.79
     840 1921.82   849.9 1924.94   859.8 1926.44   889.4  1926.7   909.2 1925.38
#Mann= 3 , 0 , 0
       0      .1       0   488.3    .045       0   503.3      .1       0
Bank Sta=488.3,503.3
XS Rating Curve= 0 ,0
Exp/Cntr=0.3,0.1

Type RM Length L Ch R = 1 ,3085.8  ,59,59.7,60.3
XS GIS Cut Line= 4
     1834660.997      219399.133      1834256.11      219451.294
     1834184.774      219451.104     1833757.162       219486.78
#Sta/Elev= 30
       0 1936.04    14.9 1928.98    44.8 1912.31    69.7 1902.34   114.5 1878.72
   144.4 1867.26   258.9 1807.46   293.7 1790.91   303.7  1788.1   323.6 1785.51
   378.4 1780.33   393.3 1777.34   408.2 1772.91   417.7 1771.81   441.5 1774.52
   479.8 1772.82   494.8 1773.92   569.4 1784.09   584.4 1788.79   609.3  1799.3
   634.2 1806.31   704.1 1848.06   724.1 1864.25     749 1889.12     759 1896.66
     774 1904.21   808.9 1918.06   828.8 1923.86   888.7 1925.58   908.7 1924.87
#Mann= 3 , 0 , 0
       0      .1       0   479.8    .045       0   494.8      .1       0
Bank Sta=479.8,494.8
XS Rating Curve= 0 ,0
Exp/Cntr=0.3,0.1

Type RM Length L Ch R = 1 ,3026.1  ,109.8,107.6,106.8
XS GIS Cut Line= 4
     1834658.057      219348.292     1834231.632      219392.276
     1834175.066       219392.06     1833753.219      219423.414
#Sta/Elev= 30
       0 1943.86    59.8 1911.89   124.6 1873.26   149.5 1863.93   204.4 1835.93
   224.3 1826.92   249.2 1812.67   294.1  1793.2     314 1783.51     344  1775.6
   403.8 1768.76   428.7 1764.76   447.5 1760.25   466.4 1753.39   473.3 1752.87
   475.8 1752.85   488.3 1754.15   564.9 1771.61   579.8 1776.55   624.6  1785.6
   649.5 1803.57   674.4 1818.84   719.2 1838.64   763.9 1864.86   813.7 1888.36
   848.5 1898.64   853.5 1899.48   873.4  1899.1   893.3    1903   908.3 1904.72
#Mann= 3 , 0 , 0
       0      .1       0   473.3    .045       0   488.3      .1       0
Bank Sta=473.3,488.3
XS Rating Curve= 0 ,0
Exp/Cntr=0.3,0.1

Type RM Length L Ch R = 1 ,2918.5  ,246.6,248.3,250
XS GIS Cut Line= 4
     1834647.099      219224.588     1834232.405      219284.046
     1834140.011      219292.179     1833746.133      219353.272
#Sta/Elev= 30
       0 1921.53    29.9 1916.04    69.8 1902.55    84.8 1896.27   144.6 1865.66
   194.5  1835.7   214.4 1826.96   314.2 1774.15   324.2 1770.84   344.1 1768.86
     409 1748.13   443.3 1731.83   443.3 1731.82     458 1727.48   458.3 1727.55
   462.9 1728.67   482.4 1738.64   501.9  1743.9   521.6 1746.63   561.5  1747.2
   586.4 1751.03   596.4  1753.7   676.1 1782.38   720.9 1805.44   750.8 1817.82
   795.7  1832.2   815.6 1837.44   870.4 1855.94   890.3 1860.45   910.3 1867.01
#Mann= 3 , 0 , 0
       0      .1       0   443.3    .045       0   458.3      .1       0
Bank Sta=443.3,458.3
XS Rating Curve= 0 ,0
Exp/Cntr=0.3,0.1

Type RM Length L Ch R = 1 ,2670.2  ,289.2,301.8,314.5
XS GIS Cut Line= 4
     1834650.995      218984.703     1834235.464      219042.381
     1834115.142       219045.44     1833736.721      219049.578
#Sta/Elev= 30
       0 1869.97      20 1863.52   134.8 1815.17   199.8 1794.78   229.7 1781.32
   289.7 1763.38   294.7  1761.1   314.6 1748.22   329.6 1747.09   334.6 1745.87
   374.6 1727.93   419.5 1698.04   429.1 1694.52     434 1694.32   440.5 1694.78
   455.5 1696.08   506.2 1703.48   549.8 1715.22   564.8 1718.41   609.6 1724.13
   629.5 1728.75   659.4 1733.82   704.2 1753.59     744 1769.35   778.9 1781.03
   803.8 1793.28   823.7 1801.19   863.5  1821.9   888.4 1831.42   918.3  1844.6
#Mann= 3 , 0 , 0
       0      .1       0   440.5    .045       0   455.5      .1       0
Bank Sta=440.5,455.5
XS Rating Curve= 0 ,0
Exp/Cntr=0.3,0.1

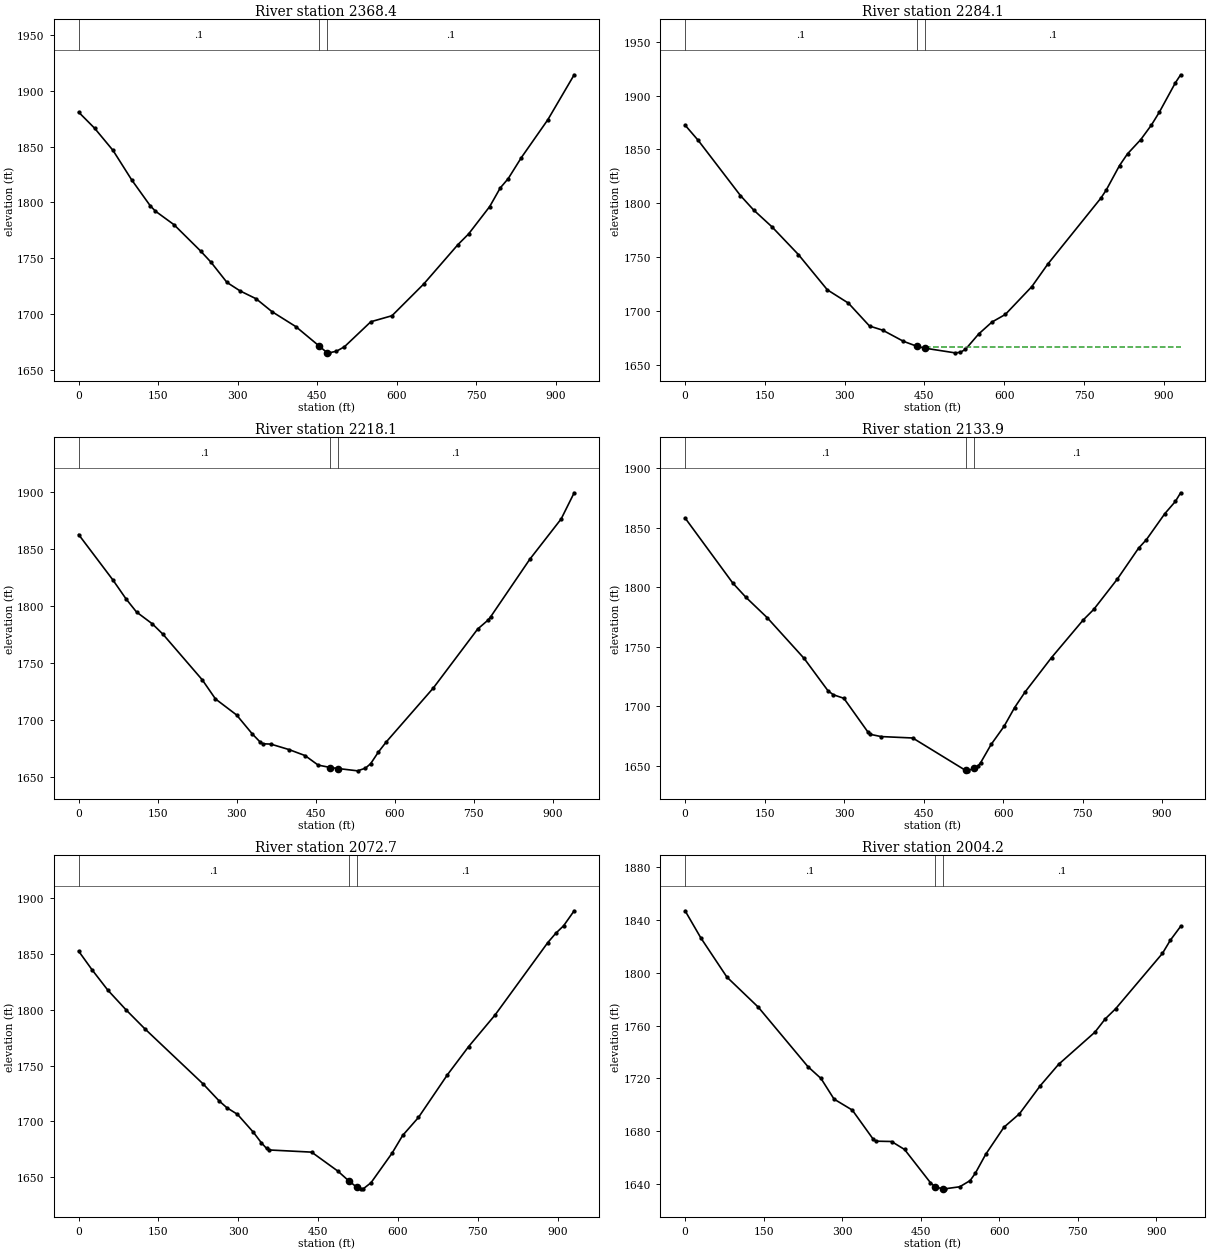
Type RM Length L Ch R = 1 ,2368.4  ,96.3,84.3,72.2
XS GIS Cut Line= 4
     1834667.941      218891.571     1834249.696      218772.362
     1834205.125      218746.068     1833764.979      218660.003
#Sta/Elev= 30
       0 1880.94      30 1866.61      65 1846.58     100 1820.34     135 1797.13
     145 1792.19     180 1780.08     230 1756.59   249.9 1746.41   279.9 1728.37
   304.9  1720.7   334.9 1713.72   364.9 1702.17   409.9 1688.76   453.9 1671.38
   468.9 1665.36   472.5 1665.27   486.6 1666.72   501.6 1670.72   551.4 1693.13
   591.3 1698.53   651.1 1726.89   715.9 1762.31   735.8 1771.76   775.7 1796.34
   795.6 1813.03   810.6 1821.36   835.5 1840.27   885.3 1874.08   935.1 1914.42
#Mann= 3 , 0 , 0
       0      .1       0   453.9    .045       0   468.9      .1       0
Bank Sta=453.9,468.9
XS Rating Curve= 0 ,0
Exp/Cntr=0.3,0.1

Type RM Length L Ch R = 1 ,2284.1  ,77.3,66,54.7
XS GIS Cut Line= 4
     1834691.559      218800.267     1834327.732      218685.748
     1834196.997      218685.748     1833784.525      218608.726
#Sta/Elev= 30
       0 1872.54    24.8 1858.35     104 1807.33   128.8 1793.93   163.5 1778.23
     213 1752.63   267.5  1719.9   307.1 1707.58   346.8 1686.35   371.5 1682.52
   410.5 1672.21   436.3  1667.5   451.3 1665.81   507.3 1661.51   517.2 1661.92
   527.1 1664.69   552.1 1679.02   577.1 1690.07   602.1 1697.06     652 1722.91
     682 1743.76   781.9 1804.95   791.9 1812.43   816.9 1835.14   831.9 1845.96
   856.8 1859.15   876.8 1872.61   891.8 1884.63   921.8 1911.71   931.8 1919.23
#Mann= 3 , 0 , 0
       0      .1       0   436.3    .045       0   451.3      .1       0
#XS Ineff= 2 , 0
                          455.27         1666.62
Permanent Ineff=
       F       F
Bank Sta=436.3,451.3
XS Rating Curve= 0 ,0
Exp/Cntr=0.3,0.1

Type RM Length L Ch R = 1 ,2218.1  ,72.9,84.2,95.4
XS GIS Cut Line= 4
     1834702.706      218760.067     1834273.006      218611.429
     1834210.879      218643.669     1833802.767      218562.783
#Sta/Elev= 30
       0  1862.6      65 1822.76    89.9 1806.16   109.9 1794.58   139.9  1784.2
   159.9 1775.17   234.8 1734.98   259.8 1718.24   299.8 1704.21   329.8 1687.46
   344.8 1680.32   349.8  1678.9   364.8 1678.62   399.7 1673.75   429.7 1668.56
   454.7 1660.17   477.8 1658.06   492.8 1657.15   529.6 1655.13   544.5 1657.49
   554.4 1661.46   569.2 1671.73   584.1 1680.59   673.3 1727.86   757.5 1779.63
   777.3 1787.53   782.2 1790.42   856.5 1840.93     916 1876.31   940.7 1899.28
#Mann= 3 , 0 , 0
       0      .1       0   477.8    .045       0   492.8      .1       0
Bank Sta=477.8,492.8
XS Rating Curve= 0 ,0
Exp/Cntr=0.3,0.1

Type RM Length L Ch R = 1 ,2133.9  ,44.4,61.2,78
XS GIS Cut Line= 4
     1834708.112       218741.15       1834267.6      218551.973
     1834150.041      218551.973     1833813.577      218519.543
#Sta/Elev= 30
       0 1858.04    89.9 1803.49   114.9 1791.42   154.8 1774.44   224.7 1740.12
   269.7 1712.99   279.7 1709.69   299.6  1706.7   344.6 1678.62   349.6 1676.46
   369.6 1674.59   429.5 1673.39   529.3 1646.16   533.3 1645.82   544.3 1647.93
   552.9 1650.05   557.8 1652.79   577.4 1667.95   601.9 1683.22   621.8 1698.98
   641.7 1712.14   691.4 1740.89   751.1 1772.42     771  1781.3   815.7 1806.87
   855.5 1832.65   870.4 1839.87   905.2 1861.72   925.1 1871.98     935 1879.22
#Mann= 3 , 0 , 0
       0      .1       0   529.3    .045       0   544.3      .1       0
Bank Sta=529.3,544.3
XS Rating Curve= 0 ,0
Exp/Cntr=0.3,0.1

Type RM Length L Ch R = 1 ,2072.7  ,67.5,68.5,69.5
XS GIS Cut Line= 4
     1834716.219      218707.368     1834277.059      218533.056
     1834218.427      218483.629     1833843.468      218412.229
#Sta/Elev= 30
       0 1852.61    24.9 1836.09    54.7 1817.73    89.5 1799.77   124.3 1783.05
   233.8 1733.64   263.6 1718.56   278.5 1712.28   298.4 1706.37   328.3  1690.3
   343.2 1680.91   353.1 1675.82   358.1 1674.44   437.7  1672.5   486.9 1655.52
     507 1646.96     522 1641.24     530 1639.61   534.8 1639.68   549.2 1645.05
   588.8 1671.58   608.7 1687.46   638.4 1703.59   692.9  1741.9   732.6 1767.07
   782.2 1795.34   881.3 1860.24   896.2 1868.54     911  1875.3   930.9 1888.76
#Mann= 3 , 0 , 0
       0      .1       0     507    .045       0     522      .1       0
Bank Sta=507,522
XS Rating Curve= 0 ,0
Exp/Cntr=0.3,0.1

Type RM Length L Ch R = 1 ,2004.2  ,295.2,278,260.9
XS GIS Cut Line= 4
     1834729.899      218659.553     1834310.302      218473.384
     1834273.248       218439.18       1833904.3      218205.398
#Sta/Elev= 30
       0 1846.94    29.9 1826.48    79.8 1796.71   139.7 1773.93   234.5 1728.85
   259.5 1719.87   284.4 1704.24   319.3  1695.9   359.2 1673.84   364.2 1672.36
   394.2 1672.11   419.1 1666.05   468.2 1641.04   477.5  1637.6   492.5 1636.27
   495.7 1636.24   524.4  1637.8   544.2 1642.49   554.1 1648.01     574  1662.4
   608.7 1682.88   638.5 1693.14   678.2 1714.39     713 1730.51   782.5 1754.95
   802.3 1765.04   822.2 1772.75   911.5 1814.67   926.4 1824.55   946.2 1835.13
#Mann= 3 , 0 , 0
       0      .1       0   477.5    .045       0   492.5      .1       0
Bank Sta=477.5,492.5
XS Rating Curve= 0 ,0
Exp/Cntr=0.3,0.1

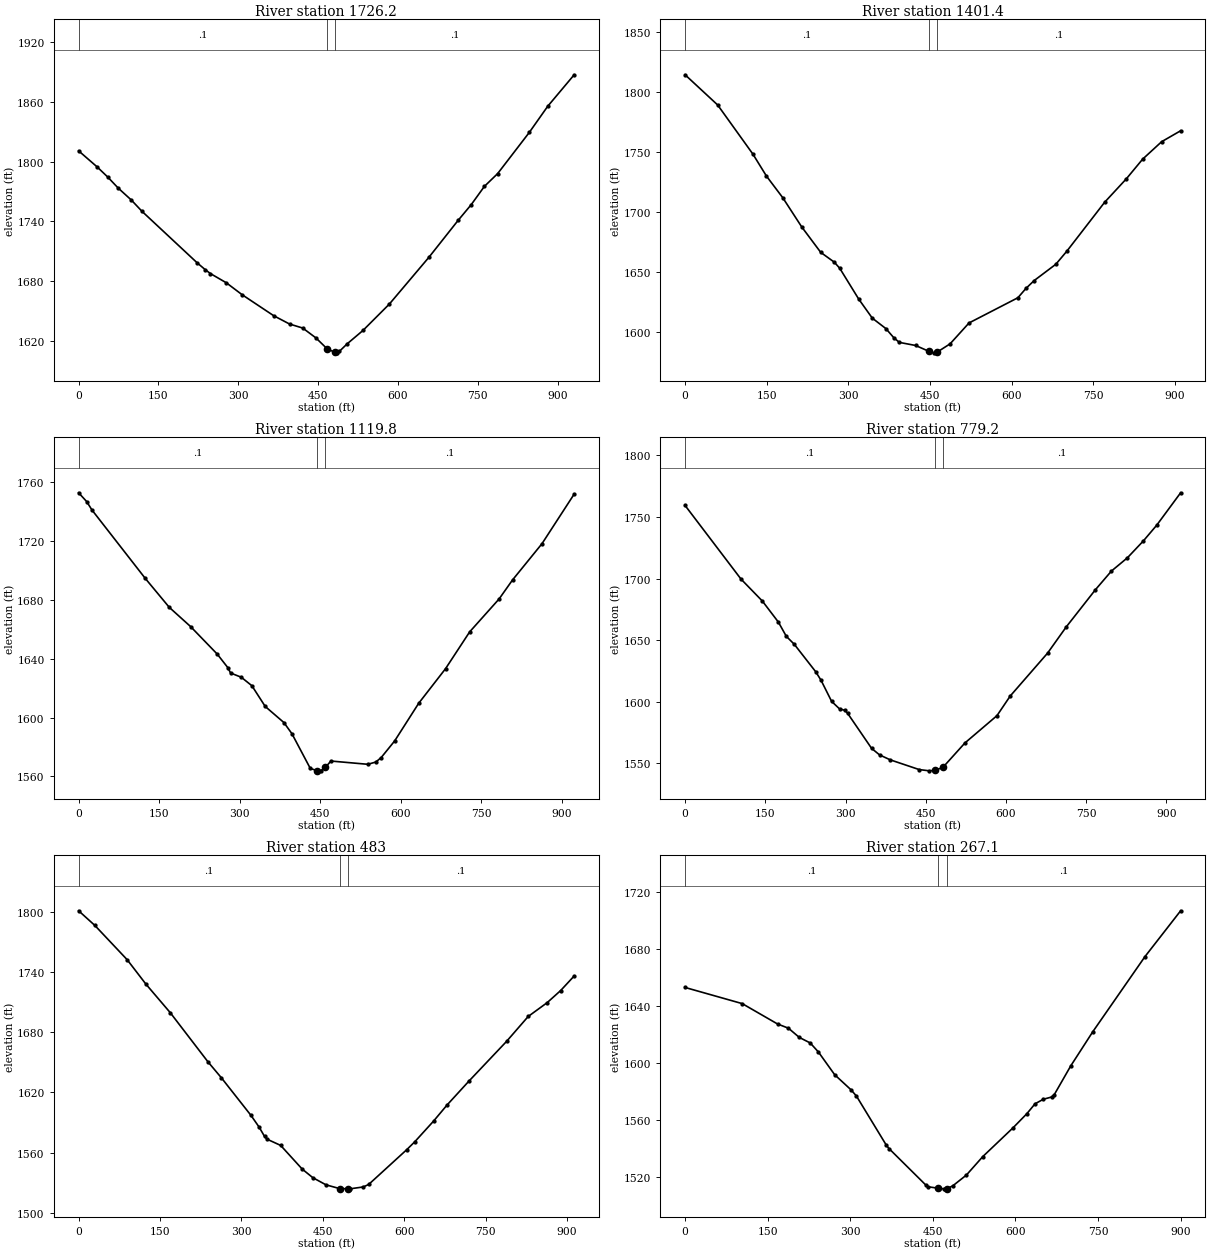
Type RM Length L Ch R = 1 ,1726.2  ,310.2,324.8,339.4
XS GIS Cut Line= 4
     1834832.602      218338.649     1834404.221      218215.419
     1834345.583      218214.053     1833945.627      218066.011
#Sta/Elev= 30
       0 1810.82    34.7 1794.72    54.5  1784.6    74.3 1773.42    99.1 1761.35
   118.9 1750.11   222.9 1698.17   237.7 1691.47   247.6 1687.47   277.4 1678.24
   307.1 1666.25   366.5 1645.11   396.2 1636.78     421 1632.72   445.8  1622.8
   466.8 1611.86   481.8 1608.24   484.9 1607.81   489.7 1609.25   504.4 1616.83
   534.2 1630.33   583.8 1656.88   658.1  1703.9   712.7 1740.83   737.5 1756.75
   762.3 1775.15   787.1 1787.93   846.6 1829.35   881.3  1855.7   930.9 1887.29
#Mann= 3 , 0 , 0
       0      .1       0   466.8    .045       0   481.8      .1       0
Bank Sta=466.8,481.8
XS Rating Curve= 0 ,0
Exp/Cntr=0.3,0.1

Type RM Length L Ch R = 1 ,1401.4  ,284.8,281.6,278.4
XS GIS Cut Line= 4
     1834905.585      218227.652     1834577.477      217967.907
     1834523.891      217925.722     1834185.784      217670.876
#Sta/Elev= 30
       0 1814.54    59.8 1789.31   124.6 1748.22   149.5 1729.85   179.4 1711.81
   214.2 1687.42   249.1 1666.16     274 1657.98     284 1652.88   318.8 1627.18
   343.8 1611.21   368.7  1602.5   383.6 1594.69   393.6 1590.94   423.4 1588.36
   447.5 1583.54   457.4 1582.22   462.5 1582.69   486.7 1589.74   521.5  1607.2
   611.2 1628.25   626.2 1636.14   641.1  1642.6   680.9 1656.24   700.9 1667.04
   770.6 1708.07   810.4 1727.63   840.3 1744.04   875.2 1758.62   910.1 1767.77
#Mann= 3 , 0 , 0
       0      .1       0   447.5    .045       0   462.5      .1       0
Bank Sta=447.5,462.5
XS Rating Curve= 0 ,0
Exp/Cntr=0.3,0.1

Type RM Length L Ch R = 1 ,1119.8  ,331,340.6,350.1
XS GIS Cut Line= 4
     1835103.101      217966.276     1834747.854      217738.717
     1834685.789      217702.827     1834294.622       217526.45
#Sta/Elev= 30
       0 1752.94    14.9 1746.99    24.8 1741.25   124.1 1694.68   168.8    1675
   208.5 1661.92   258.1  1643.2   277.9 1633.94   282.9 1630.34   302.8 1627.47
   322.6 1621.69   347.4  1607.6   382.2 1596.64   397.1 1589.08   431.4 1565.41
   444.6 1563.85   450.6 1563.79   459.6 1566.18   469.7 1570.46   538.5 1568.24
   553.4 1569.78   563.4 1572.85   588.4 1584.11   633.3  1609.8   683.2 1633.29
   728.1 1658.32     783 1680.75   807.9 1693.63   862.8 1718.32   922.7 1752.04
#Mann= 3 , 0 , 0
       0      .1       0   444.6    .045       0   459.6      .1       0
Bank Sta=444.6,459.6
XS Rating Curve= 0 ,0
Exp/Cntr=0.3,0.1

Type RM Length L Ch R = 1 ,779.2   ,300.2,296.2,291.9
XS GIS Cut Line= 4
     1835211.149      217757.894     1834892.722      217478.792
     1834834.006      217397.843     1834576.355      217087.608
#Sta/Elev= 30
       0 1759.33   104.6  1699.5   144.5 1681.67   174.4 1664.61   189.3    1653
   204.2 1646.54   244.1 1624.32   254.1 1617.42     274 1600.16   288.9 1594.01
   298.9  1592.9   303.9 1590.48   348.7 1562.01   363.6 1556.68   383.6 1552.65
   437.7 1544.75   456.8 1543.71     467 1544.14     482 1546.47   523.4 1566.41
   583.2 1588.54   608.1 1604.56   677.8 1639.33   712.6 1660.57   767.4 1690.92
   797.3 1706.06   827.1 1716.81     857 1730.54   881.9 1743.28   926.7 1769.66
#Mann= 3 , 0 , 0
       0      .1       0     467    .045       0     482      .1       0
Bank Sta=467,482
XS Rating Curve= 0 ,0
Exp/Cntr=0.3,0.1

Type RM Length L Ch R = 1 ,483     ,217.3,215.9,211
XS GIS Cut Line= 4
     1835417.236      217566.006     1835119.037      217281.551
      1835048.92      217213.713     1834723.305      216974.971
#Sta/Elev= 30
       0 1801.04    29.8 1786.48    89.4  1752.3   124.1 1727.86   168.8 1699.51
   238.3  1650.5   263.2 1634.48   317.8 1596.96   332.7 1585.35   342.6 1576.14
   347.6 1573.25   372.4 1567.11   412.1 1543.51   431.6 1534.97     456  1527.8
   481.1 1524.06   496.1 1523.89   499.9 1523.82   524.6 1525.69   534.6 1528.18
   604.4 1562.67   619.3 1570.57   654.2 1591.34   679.2 1607.46     719 1630.98
   788.8 1670.84   828.7 1695.69   863.6 1709.43   888.5 1721.52   913.4 1736.03
#Mann= 3 , 0 , 0
       0      .1       0   481.1    .045       0   496.1      .1       0
Bank Sta=481.1,496.1
XS Rating Curve= 0 ,0
Exp/Cntr=0.3,0.1

Type RM Length L Ch R = 1 ,267.1   ,149.4,149.9,153
XS GIS Cut Line= 4
     1835576.235      217358.474     1835269.108      217134.154
     1835220.223       217076.38     1834839.587      216847.745
#Sta/Elev= 30
       0 1652.94   103.7 1641.62   167.9 1627.33   187.7 1624.37   207.4 1617.91
   227.2 1614.03     242 1607.75   271.7 1591.73   301.3 1581.18   311.2 1576.77
   365.5  1542.3   370.4 1539.92   437.1  1514.4   441.8 1513.11     460 1512.12
     471  1511.7     475 1511.79   485.9 1513.72   510.9 1521.37   540.8 1534.37
   595.7 1554.54   620.6 1564.36   635.6 1571.36   650.6 1574.53   665.5 1576.09
   670.5 1577.77   700.5 1597.99   740.4 1621.87   835.2 1674.58     900 1706.73
#Mann= 3 , 0 , 0
       0      .1       0     460    .045       0     475      .1       0
Bank Sta=460,475
XS Rating Curve= 0 ,0
Exp/Cntr=0.3,0.1

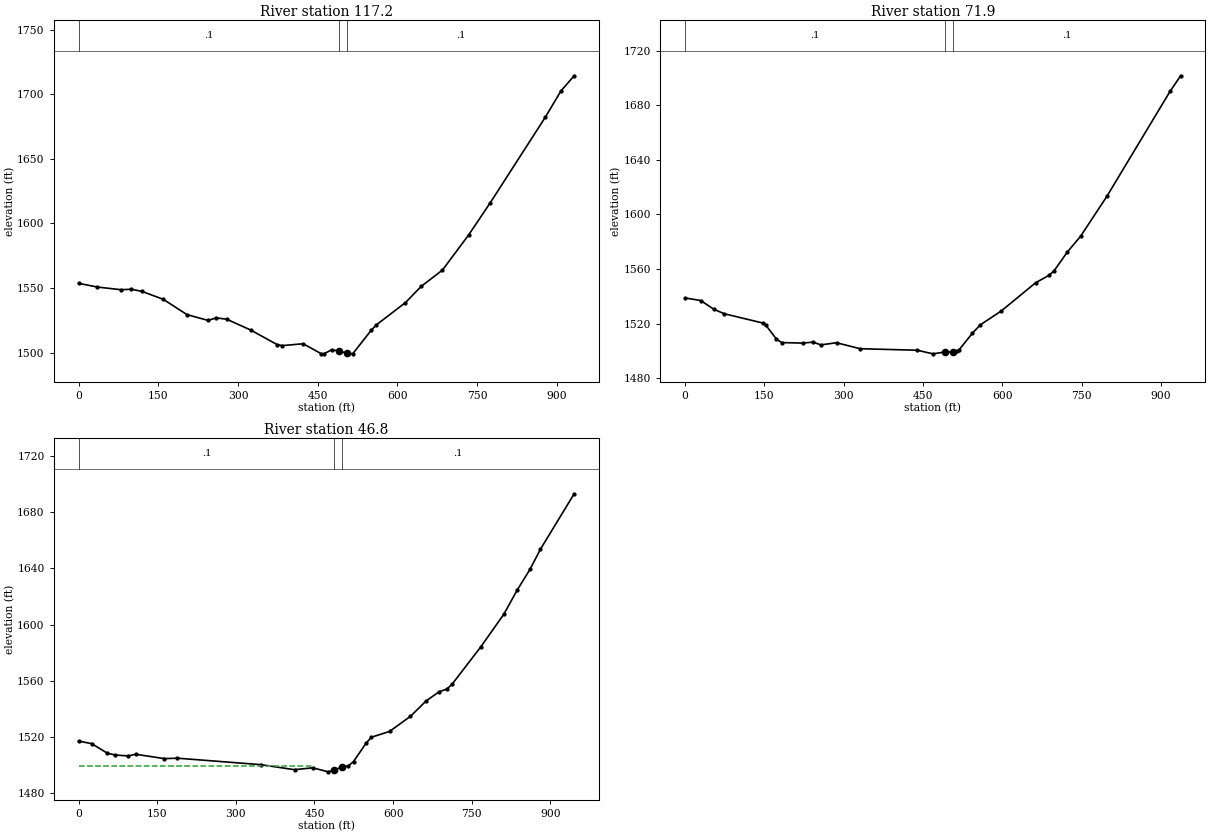
Type RM Length L Ch R = 1 ,117.2   ,52.9,45.3,37.2
XS GIS Cut Line= 4
     1835676.124      217243.419     1835360.404      217009.068
     1835269.312      216926.814      1834881.98      216772.968
#Sta/Elev= 30
       0 1553.66    34.8 1550.78    79.6 1548.69    99.5 1549.06   119.4 1547.36
   159.3 1541.25   204.1 1529.35   243.9 1524.89   258.8 1526.88   278.7 1525.83
   323.5 1517.52   373.3 1506.24   383.2 1505.37   422.6 1506.83     457 1499.01
   461.9 1499.08   476.6 1502.23   489.4 1501.12   504.4 1499.67   515.9 1499.03
   550.7 1517.29   560.6 1521.53   615.2 1538.71   644.9 1551.33   684.6 1563.82
   734.2 1591.18   773.9 1615.51   878.1 1682.13   907.9 1702.72   932.7 1714.42
#Mann= 3 , 0 , 0
       0      .1       0   489.4    .045       0   504.4      .1       0
Bank Sta=489.4,504.4
XS Rating Curve= 0 ,0
Exp/Cntr=0.3,0.1

Type RM Length L Ch R = 1 ,71.9    ,26,25.1,26.1
XS GIS Cut Line= 4
     1835689.568      217224.687     1835422.944      216989.355
     1835328.453      216910.499     1834900.844      216744.417
#Sta/Elev= 30
       0 1538.78    29.6 1536.88    54.3  1530.5    74.1  1527.2   148.2 1520.28
   153.1 1518.63   172.9 1508.55   182.8 1506.06   222.3 1505.69     242 1506.39
   256.8 1504.38   286.5 1505.94   330.9 1501.57   439.3 1500.45   468.8 1497.81
   491.5 1499.14   506.5 1499.21   513.6 1499.55   518.6 1500.91   543.5 1512.94
   558.5 1519.06   598.4 1529.32   663.2 1549.94   688.1  1555.3   698.1 1558.71
     723 1572.42     748 1583.92   797.8 1613.22   917.5 1690.27   937.4 1701.62
#Mann= 3 , 0 , 0
       0      .1       0   491.5    .045       0   506.5      .1       0
Bank Sta=491.5,506.5
XS Rating Curve= 0 ,0
Exp/Cntr=0.3,0.1

Type RM Length L Ch R = 1 ,46.8    ,33.5,46.8,60.1
XS GIS Cut Line= 5
      1835707.68      217205.536     1835456.933      216979.838
     1835360.404      216901.662     1835276.074      216865.014
     1834911.909      216719.993
#Sta/Elev= 30
       0 1516.92    24.8 1515.12    54.6 1508.36    69.5 1507.02    94.3 1506.36
   109.2 1507.52   163.7 1504.44   188.5 1504.75   347.3 1500.15   411.9 1496.56
   446.7  1497.9   476.1 1495.02   487.4 1496.24   502.4 1498.51   514.8 1499.28
   524.5 1502.38   548.7 1515.57   558.5 1519.67   593.2 1523.81   632.9 1534.52
   662.7 1545.44   687.5 1552.04   702.4 1553.96   712.3 1557.35   766.9 1583.87
   811.5 1607.47   836.4 1624.35   861.2 1639.34     881 1653.59   945.5  1693.2
#Mann= 3 , 0 , 0
       0      .1       0   487.4    .045       0   502.4      .1       0
#XS Ineff= 2 , 0
          443.85 1499.47
Permanent Ineff=
       F       F
Bank Sta=487.4,502.4
XS Rating Curve= 0 ,0
Exp/Cntr=0.3,0.1

Chan Stop Cuts=-1
Use User Specified Reach Order=0